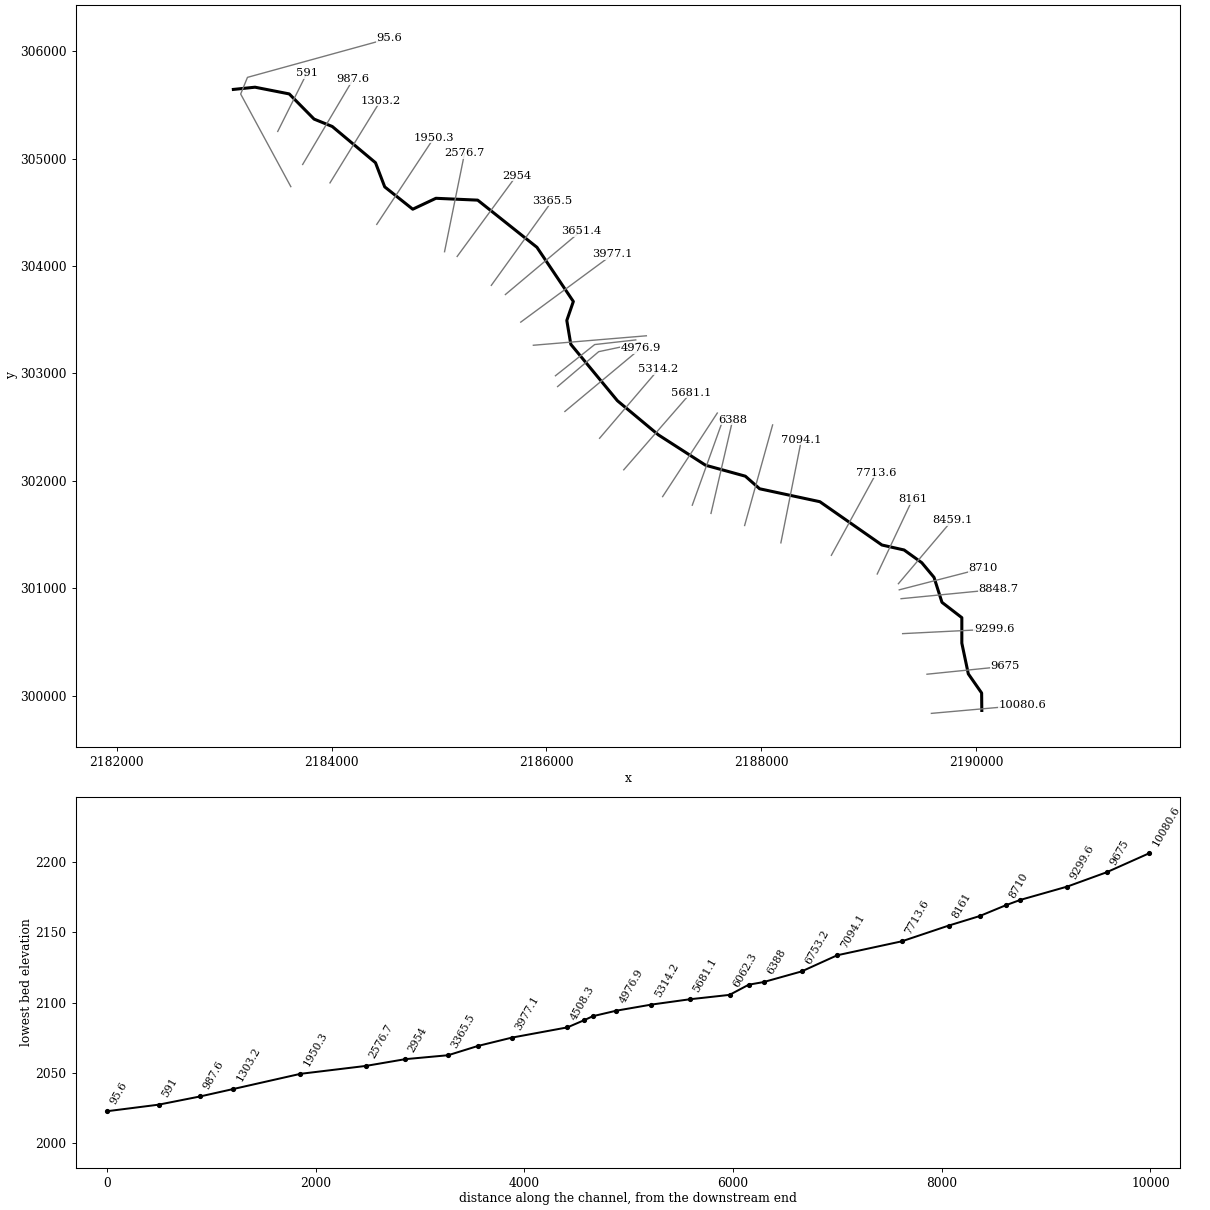
--- SlphrLkRun.prj (project) ---

Proj Title=SlphrLkRun
Current Plan=p01
Geom File=g01
Flow File=f01
Plan File=p01
DSS Export Rating Curves=0
DSS Export Rating Curve Sorted=0
DSS Export Volume Flow Curves=0
DXF OffsetX=0
DXF OffsetY=0
DXF ScaleX=0
DXF ScaleY=0

--- SlphrLkRun.p01 (plan) ---

Plan Title=Floodplain
Program Version=4.00
Geom File=g01
Flow File=f01
K Sum by GR=0
Std Step Tol=0.01
Critical Tol=0.01
Num of Std Step Trials=20
Max Error Tol=0.3
Flow Tol Ratio=0.001
Split Flow NTrial=30
Split Flow Tol=0.02
Split Flow Ratio=0.02
Log Output Level=0
Friction Slope Method=1
Unsteady Friction Slope Method=2
Unsteady Bridges Friction Slope Method=1
Global Log Level=0
CheckData=False
Run HTab=0
Run UNet=0
Run PostProcess=0
UNET Theta=0
UNET Theta Warmup=0
UNET ZTol=0
UNET ZSATol=0
UNET MxIter=0
UNET MaxInSteps=0
UNET DtIC=0
UNET DtMin=0
UNET MaxCRTS=0
UNET WFStab=0
UNET SFStab=0
UNET WFX=0
UNET SFX=0
UNET DSS MLevel=0
UNET DZMax Abort=0
UNET Convert EG Bridges=0
UNET Use Existing IB Tables=0
UNET Froude Limit=0
UNET Froude Power=0
Write IC File=0
Echo Input=False
Echo Output=False
Write Detailed=0

--- SlphrLkRun.f01 (steady flow) ---

Flow Title=NFF Regression Equation
Program Version=4.00
Number of Profiles=1
Profile Names=P100yr
River Rch & RM=SlphrLkRun,Main      ,10080.6
519.1744
River Rch & RM=SlphrLkRun,Main      ,8848.7
576.2684
River Rch & RM=SlphrLkRun,Main      ,7713.6
618.1708
River Rch & RM=SlphrLkRun,Main      ,3977.1
686.4870
River Rch & RM=SlphrLkRun,Main      ,3651.4
1031.286
River Rch & RM=SlphrLkRun,Main      ,95.6
1122.548
Boundary for River Rch & Prof#=SlphrLkRun,Main      ,1
Up Type=0
Dn Type=3
Dn Slope=0.013478

--- SlphrLkRun.g01 (geometry) ---

Geom Title=USGS 10m DEM
Program Version=4.10

River Reach=SlphrLkRun      ,Main
Reach XY= 30
     2190053.219      299862.263     2190051.656      300024.763
     2189927.608      300202.921     2189867.281      300488.826
     2189867.281      300726.325     2189682.375      300868.946
     2189608.311      301101.561     2189494.198      301238.168
      2189329.78      301356.405      2189123.33      301402.754
     2188545.406      301806.013     2187984.469      301926.326
     2187851.656      302043.513     2187481.309      302145.586
     2187042.281      302427.888     2186660.333      302746.176
     2186226.614      303271.356     2186189.156      303493.513
     2186250.094      303670.075     2185911.031      304174.763
     2185359.469      304613.826     2184970.406      304631.013
     2184754.781      304529.451     2184493.844      304737.263
     2184407.906      304962.263     2184005.523      305299.515
     2183836.031      305368.513     2183604.781      305602.888
     2183286.031      305665.388     2183084.433      305644.607

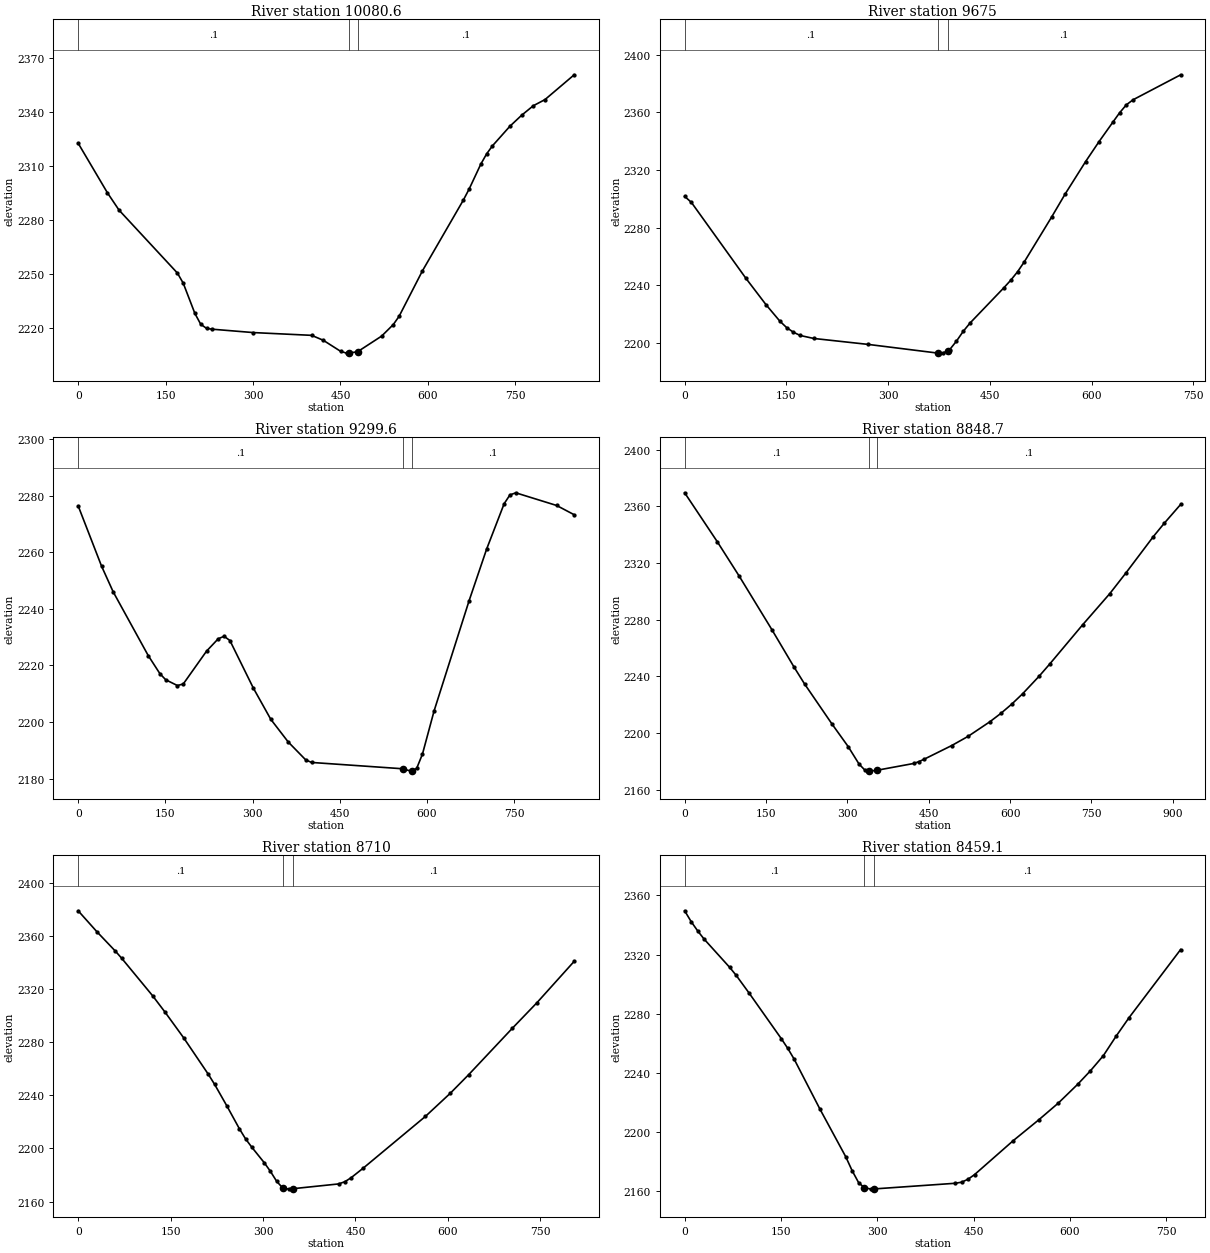
Type RM Length L Ch R = 1 ,10080.6 ,404.7,405.6,406.5
XS GIS Cut Line= 2
     2189583.841        299835.1     2190431.447      299910.662
#Sta/Elev= 30
       0  2322.8    50.1 2295.33    70.1 2285.68   170.2 2250.74   180.2 2245.12
   200.2 2228.31   210.2 2222.31   220.2 2220.01   230.3 2219.54   300.3 2217.68
   400.5 2216.14   420.5  2213.4   450.5 2207.22   460.5 2206.26   464.5 2206.27
   479.5 2207.06   520.6 2215.71   540.6 2222.11   550.6 2226.71   590.7 2251.99
   660.8 2291.23   670.8  2297.4   690.8 2311.22   700.8 2316.93   710.8 2321.41
   740.8  2332.3   760.9  2338.4   780.9 2343.68   800.9 2347.08     851 2360.85
#Mann= 3 , 0 , 0
       0      .1       0   464.5    .045       0   479.5      .1       0
Bank Sta=464.5,479.5
XS Rating Curve= 0 ,0
Exp/Cntr=0.3,0.1

Type RM Length L Ch R = 1 ,9675    ,376.7,375.4,374
XS GIS Cut Line= 2
     2189542.774      300199.768     2190270.467      300273.687
#Sta/Elev= 30
       0 2301.61      10 2297.36    90.2 2244.79   120.2 2226.27   140.3 2215.02
   150.3 2210.55   160.3 2207.31   170.3 2205.05   190.4 2202.97   270.5 2198.85
     373 2192.83   380.8 2192.79     388 2194.54   390.8 2195.22   400.8  2201.1
   410.8 2207.92   420.8 2213.66   470.9 2238.25     481 2243.47     491 2249.33
     501 2256.27   541.1 2287.22   561.1 2303.24   591.2 2325.72   611.2  2339.7
   631.2 2352.94   641.3 2359.56   651.3 2365.15   661.3 2368.68   731.4 2385.99
#Mann= 3 , 0 , 0
       0      .1       0     373    .045       0     388      .1       0
Bank Sta=373,388
XS Rating Curve= 0 ,0
Exp/Cntr=0.3,0.1

Type RM Length L Ch R = 1 ,9299.6  ,449.9,450.9,451.9
XS GIS Cut Line= 2
     2189316.089      300577.576     2190168.623      300620.285
#Sta/Elev= 30
       0 2276.41    40.2 2255.12    60.2 2246.04   120.5 2223.51   140.6 2217.11
   150.6 2214.95   170.7 2212.91   180.8 2213.46   220.9 2225.08     241 2229.45
   251.1 2230.33   261.1 2228.82   301.3 2212.06   331.4 2200.98   361.5 2192.94
   391.6 2186.61   401.7 2185.71   558.9 2183.47   572.4 2182.64   573.9 2182.78
   582.5 2183.58   592.5 2188.66   612.6 2203.99   672.8 2242.92     703 2261.19
   733.1 2277.21   743.1 2280.33   753.2 2281.06   823.5 2276.58   853.6 2273.32
#Mann= 3 , 0 , 0
       0      .1       0   558.9    .045       0   573.9      .1       0
Bank Sta=558.9,573.9
XS Rating Curve= 0 ,0
Exp/Cntr=0.3,0.1

Type RM Length L Ch R = 1 ,8848.7  ,134.6,138.8,142.5
XS GIS Cut Line= 2
     2189301.305      300902.821     2190211.332      300991.524
#Sta/Elev= 30
       0  2369.6    60.3 2334.97   100.5 2310.81   160.8 2272.98     201 2246.98
     221 2234.68   271.3 2206.54   301.4 2190.45   321.5 2178.09   331.6 2174.09
   340.3 2173.25   341.6 2173.12   355.3 2173.79     422 2178.51     432 2179.85
   442.1 2181.65   492.3 2191.18   522.5 2197.67   562.7 2207.99   582.8 2213.85
   602.9  2220.4     623 2227.73   653.1 2239.99   673.2 2248.83   733.5 2276.36
   783.7 2298.42   813.9 2313.26   864.1 2338.75   884.2 2348.15   914.3 2361.38
#Mann= 3 , 0 , 0
       0      .1       0   340.3    .045       0   355.3      .1       0
Bank Sta=340.3,355.3
XS Rating Curve= 0 ,0
Exp/Cntr=0.3,0.1

Type RM Length L Ch R = 1 ,8710    ,236.8,250.8,264.7
XS GIS Cut Line= 2
     2189284.598      300985.413     2190064.047      301186.747
#Sta/Elev= 30
       0 2378.86    30.2 2363.19    60.4 2348.48    70.4 2343.24   120.8  2314.9
   140.9  2302.6   171.1 2283.29   211.3 2255.71   221.4  2248.2   241.5 2231.79
   261.6 2214.79   271.7 2207.12   281.8 2200.86   301.9 2189.26     312  2182.7
     322 2175.29   332.1 2170.08     333 2170.01   342.1 2169.32     348 2169.62
   422.6 2173.23   432.7 2174.88   442.8 2177.84   462.9 2185.22   563.5 2224.04
   603.8 2241.43     634  2255.6   704.4 2290.31   744.6 2309.68     805 2340.81
#Mann= 3 , 0 , 0
       0      .1       0     333    .045       0     348      .1       0
Bank Sta=333,348
XS Rating Curve= 0 ,0
Exp/Cntr=0.3,0.1

Type RM Length L Ch R = 1 ,8459.1  ,292.4,298.1,304
XS GIS Cut Line= 2
     2189276.666      301042.446      2189776.03      301632.156
#Sta/Elev= 30
       0 2349.57      10 2342.34    20.1 2336.11    30.1 2330.56    70.2 2311.34
    80.3 2305.96   100.4 2294.01   150.5 2263.25   160.6 2256.68   170.6 2249.37
   210.8 2215.61   250.9 2183.51   260.9 2174.07     271 2165.98     280 2162.53
     291  2161.6     295 2161.73   421.5 2165.55   431.5 2166.28   441.6 2168.32
   451.6 2171.39   511.8 2194.31     552 2208.52   582.1  2219.7   612.2 2232.35
   632.2 2241.53   652.3 2251.74   672.4 2265.04   692.4 2277.44   772.7 2323.41
#Mann= 3 , 0 , 0
       0      .1       0     280    .045       0     295      .1       0
Bank Sta=280,295
XS Rating Curve= 0 ,0
Exp/Cntr=0.3,0.1

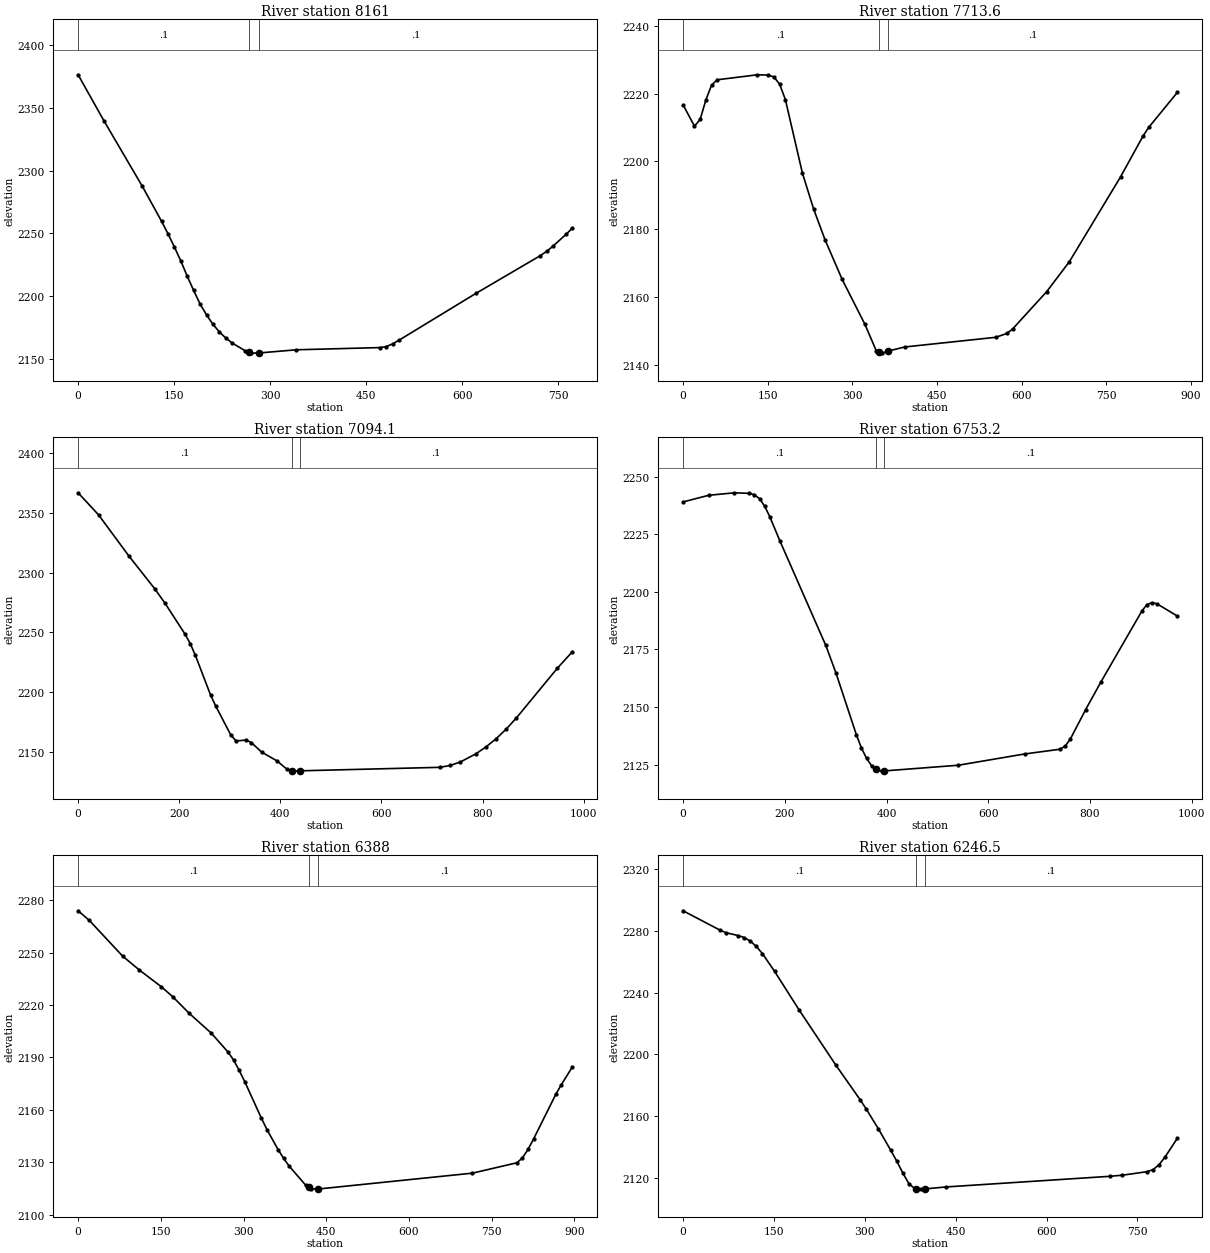
Type RM Length L Ch R = 1 ,8161    ,448.4,447.4,446
XS GIS Cut Line= 2
     2189079.548      301132.791      2189409.72      301830.916
#Sta/Elev= 30
       0 2376.26    40.1 2339.88   100.3 2287.53   130.4 2259.67   140.4 2249.75
   150.4  2239.3   160.5 2228.04   170.5 2215.98   180.5 2204.66   190.6 2193.81
   200.6 2185.25   210.6 2177.77   220.6 2171.67   230.7 2166.82   240.7 2162.83
   260.8 2156.72   267.7 2155.39   270.8 2154.79   282.7 2154.92     341 2157.45
   471.4  2159.2   481.4    2160   491.4 2162.18   501.5 2165.12   621.8 2202.42
   722.1 2232.36   732.2 2235.87   742.2 2240.06   762.2 2249.26   772.3 2254.31
#Mann= 3 , 0 , 0
       0      .1       0   267.7    .045       0   282.7      .1       0
Bank Sta=267.7,282.7
XS Rating Curve= 0 ,0
Exp/Cntr=0.3,0.1

Type RM Length L Ch R = 1 ,7713.6  ,612.4,619.5,626.3
XS GIS Cut Line= 2
      2188652.46      301306.912     2189072.977      302075.671
#Sta/Elev= 30
       0 2216.66    20.1  2210.4    30.2 2212.37    40.3 2218.09    50.4 2222.46
    60.4 2224.04   130.9  2225.5   151.1 2225.44   161.2 2224.82   171.2  2222.7
   181.3 2218.19   211.5 2196.56   231.6  2185.9   251.8 2176.88     282 2165.29
   322.3 2152.09   342.4 2144.31   347.8 2143.94   352.5 2143.62   362.8  2144.2
   392.8 2145.43     554 2148.27   574.1 2149.41   584.2 2150.74   644.6 2161.73
   684.9 2170.56   775.5 2195.48   815.8 2207.63   825.9 2210.14   876.3 2220.35
#Mann= 3 , 0 , 0
       0      .1       0   347.8    .045       0   362.8      .1       0
Bank Sta=347.8,362.8
XS Rating Curve= 0 ,0
Exp/Cntr=0.3,0.1

Type RM Length L Ch R = 1 ,7094.1  ,342.3,340.9,340
XS GIS Cut Line= 2
     2188182.471      301422.878     2188373.302      302381.929
#Sta/Elev= 30
       0 2366.95    40.3 2348.54   100.8 2313.77   151.2 2286.69   171.4  2274.7
   211.7 2248.35   221.8  2240.5   231.9 2230.76   262.1 2197.32   272.2  2188.2
   302.4 2163.62   312.5 2159.01   332.7 2159.68   342.8 2157.55   362.9 2149.65
   393.2  2142.3   413.3 2135.17   423.4 2133.67   423.8 2133.67   438.8 2133.92
   715.8 2136.86   735.9 2138.41   756.1 2141.33   786.3 2148.05   806.5 2153.89
   826.6 2160.75   846.8  2168.9     867 2178.29   947.6 2219.75   977.8 2233.82
#Mann= 3 , 0 , 0
       0      .1       0   423.8    .045       0   438.8      .1       0
Bank Sta=423.8,438.8
XS Rating Curve= 0 ,0
Exp/Cntr=0.3,0.1

Type RM Length L Ch R = 1 ,6753.2  ,364.4,365.2,365
XS GIS Cut Line= 2
     2187844.846      301584.351     2188105.458      302520.828
#Sta/Elev= 30
       0  2239.1    50.1 2241.97   100.2 2243.05   130.3 2242.84   140.3  2242.2
   150.3 2240.49   160.3 2237.29   170.4 2232.68   190.4 2222.12   280.6 2176.76
   300.6 2164.77   340.7 2137.96   350.7 2132.19   360.8 2127.68   370.8 2124.48
   379.5 2122.93   390.8 2122.16   394.5 2122.23   541.2 2124.72   671.4 2129.61
   741.6 2131.68   751.6 2133.09   761.6 2136.15   791.7 2148.92   821.7 2160.92
   901.9  2191.6   911.9 2194.46     922 2195.39     932 2194.83   972.1  2189.5
#Mann= 3 , 0 , 0
       0      .1       0   379.5    .045       0   394.5      .1       0
Bank Sta=379.5,394.5
XS Rating Curve= 0 ,0
Exp/Cntr=0.3,0.1

Type RM Length L Ch R = 1 ,6388    ,144.2,141.5,138.9
XS GIS Cut Line= 2
     2187531.687      301696.893     2187734.329      302570.197
#Sta/Elev= 30
       0 2273.91    20.2 2268.47    80.6    2248   110.8 2240.08   151.1 2230.39
   171.2 2224.84   201.5 2215.21   241.8 2203.78     272 2192.99     282 2188.46
   292.1 2182.57   302.2 2176.09   332.4 2155.16   342.5 2148.63   362.6 2137.23
   372.7 2132.18   382.8 2127.71     413 2116.72   419.6 2115.51   423.1 2114.87
   433.1 2114.56   434.6  2114.6   715.2 2123.71   795.8 2129.65   805.8 2132.42
   815.9 2137.28     826 2143.26   866.3 2168.82   876.4  2174.4   896.5 2184.61
#Mann= 3 , 0 , 0
       0      .1       0   419.6    .045       0   434.6      .1       0
Bank Sta=419.6,434.6
XS Rating Curve= 0 ,0
Exp/Cntr=0.3,0.1

Type RM Length L Ch R = 1 ,6246.5  ,189.4,184.1,178.9
XS GIS Cut Line= 2
     2187357.547      301773.491     2187633.662      302541.435
#Sta/Elev= 30
       0 2293.15    60.4 2280.72    70.5 2279.01    90.7 2277.12   100.8 2275.85
   110.8 2273.56   120.9 2270.04     131 2265.39   151.1 2253.85   191.4 2228.95
   251.9 2193.25   292.2 2170.71   302.2 2164.72   322.4 2151.78   342.6 2138.01
   352.6 2130.97   362.7 2123.17   372.8 2116.18   382.8 2112.97   384.1 2112.94
   392.9 2112.71   399.1 2112.85   433.2  2114.1   705.2 2121.04   725.4 2121.76
   765.7    2124   775.8 2125.32   785.8 2128.54   795.9 2133.68   816.1 2145.75
#Mann= 3 , 0 , 0
       0      .1       0   384.1    .045       0   399.1      .1       0
Bank Sta=384.1,399.1
XS Rating Curve= 0 ,0
Exp/Cntr=0.3,0.1

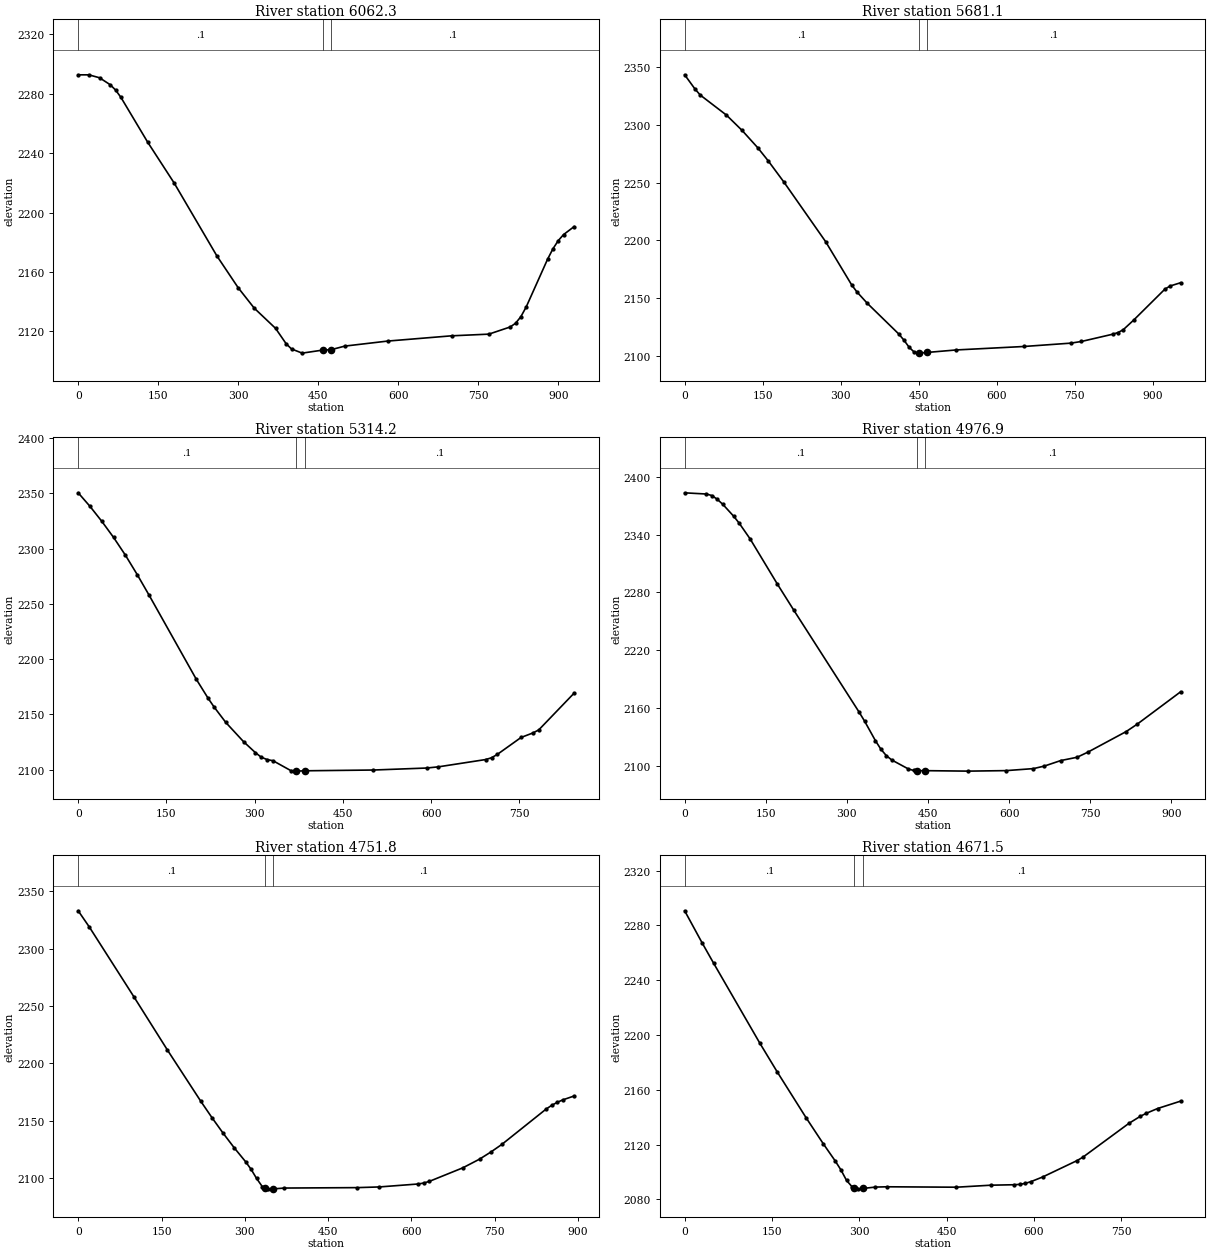
Type RM Length L Ch R = 1 ,6062.3  ,384.3,381.2,378
XS GIS Cut Line= 2
      2187081.52      301853.472     2187590.404      302631.478
#Sta/Elev= 30
       0 2292.62      20 2292.61      40 2290.64      60 2285.95      70 2282.41
      80 2277.49     130 2247.44   179.9 2219.82   259.9 2170.84   299.9 2149.39
   329.9 2135.71   369.9 2122.11   389.8 2111.73   399.8 2108.25   419.8 2105.44
   458.6  2107.5   473.6 2107.71   499.8 2110.17   579.8 2113.54   699.7 2117.08
   769.7 2118.21   809.7 2123.03   819.7 2125.51   829.7 2129.93   839.7 2136.48
   879.7 2168.53   889.7 2175.52   899.7 2181.07   909.7 2185.16   929.6 2190.55
#Mann= 3 , 0 , 0
       0      .1       0   458.6    .045       0   473.6      .1       0
Bank Sta=458.6,473.6
XS Rating Curve= 0 ,0
Exp/Cntr=0.3,0.1

Type RM Length L Ch R = 1 ,5681.1  ,366.7,366.9,367.1
XS GIS Cut Line= 2
     2186719.429      302103.021     2187345.748      302822.309
#Sta/Elev= 30
       0 2343.59    20.1 2331.12    30.1    2326    80.3 2308.68   110.4  2295.4
   140.6 2280.35   160.6 2269.05   190.8 2250.64   271.1 2198.94   321.3 2161.35
   331.3 2155.37   351.4 2145.42   411.6 2118.97   421.7 2113.55   431.7 2107.38
   441.7 2103.09   450.6  2102.4   451.8 2102.31   465.6 2102.88   522.1 2105.06
   652.6 2108.07   742.9 2110.98     763 2112.41   823.2 2118.71   833.3 2120.13
   843.3 2122.54   863.4  2130.9   923.6  2157.8   933.7 2160.52   953.8 2163.34
#Mann= 3 , 0 , 0
       0      .1       0   450.6    .045       0   465.6      .1       0
Bank Sta=450.6,465.6
XS Rating Curve= 0 ,0
Exp/Cntr=0.3,0.1

Type RM Length L Ch R = 1 ,5314.2  ,341.1,337.3,333.5
XS GIS Cut Line= 2
     2186494.346      302396.608     2187042.375      303037.606
#Sta/Elev= 30
       0 2350.54    20.1 2338.23    40.2 2324.68    60.2  2310.1    80.3 2294.03
   100.4 2276.44   120.5 2257.88   200.8  2181.7   220.9 2164.49   230.9  2156.7
     251 2142.59   281.1 2125.24   301.2 2115.32   311.2 2111.15   321.3 2108.98
   331.3 2107.94   361.4 2099.04   369.9 2098.61   371.5 2098.53   384.9 2098.83
     502 2099.53   592.3 2101.33   612.4 2102.41   692.7 2109.01   702.8 2110.63
   712.8 2113.73     753 2129.01   773.1 2133.09   783.1 2135.85   843.3 2169.19
#Mann= 3 , 0 , 0
       0      .1       0   369.9    .045       0   384.9      .1       0
Bank Sta=369.9,384.9
XS Rating Curve= 0 ,0
Exp/Cntr=0.3,0.1

Type RM Length L Ch R = 1 ,4976.9  ,224.9,225.1,225.3
XS GIS Cut Line= 2
       2186171.4      302646.157     2186876.009      303233.331
#Sta/Elev= 30
       0 2383.69    40.3 2382.44    50.4 2380.85    60.5 2376.85    70.6 2371.66
    90.7  2359.3   100.8 2352.12     121 2335.78   171.3 2288.87   201.6 2261.77
   322.5 2155.64   332.6  2146.3   352.8 2125.82   362.8 2117.03   372.9  2110.3
     383 2105.75   413.2 2096.59   423.3 2094.83     430 2094.58     445 2094.66
   524.1 2094.17   594.7  2094.7   645.1  2096.8   665.2 2099.43   695.5 2105.16
   725.7 2108.59   745.8 2113.95   816.4 2135.29   836.6 2142.89   917.2  2176.7
#Mann= 3 , 0 , 0
       0      .1       0     430    .045       0     445      .1       0
Bank Sta=430,445
XS Rating Curve= 0 ,0
Exp/Cntr=0.3,0.1

Type RM Length L Ch R = 1 ,4751.8  ,81,80.2,79.5
XS GIS Cut Line= 3
     2186103.526      302877.949      2186486.06      303202.959
     2186868.594      303283.493
#Sta/Elev= 30
       0 2333.03    20.1 2318.86   100.4 2257.92   160.6  2211.6   220.9 2166.75
   240.9 2152.53     261 2138.97   281.1 2126.16   301.2 2114.26   311.2 2107.57
   321.2 2099.52   331.3 2092.52   335.7 2091.52   341.3 2090.24   350.7 2090.44
   371.4 2091.18     502 2091.55     542 2092.14   612.2 2094.73   622.2 2095.57
   632.3 2097.03   692.4 2108.81   722.5 2116.38   742.5 2122.47   762.6  2129.2
   842.8 2160.23   852.8 2163.43   862.8 2166.04   872.8 2168.17   892.9  2171.5
#Mann= 3 , 0 , 0
       0      .1       0   335.7    .045       0   350.7      .1       0
Bank Sta=335.7,350.7
XS Rating Curve= 0 ,0
Exp/Cntr=0.3,0.1

Type RM Length L Ch R = 1 ,4671.5  ,177.4,163.2,149
XS GIS Cut Line= 3
     2186083.393      302978.616      2186448.67      303269.112
     2186831.204      303312.255
#Sta/Elev= 30
       0  2290.6    29.8 2267.33    49.6 2252.44   129.1 2193.98   158.9 2173.05
   208.5 2139.59   238.3 2120.41   258.2 2108.26   268.1 2101.67     278 2093.84
     288 2088.92   291.5 2088.41   297.9 2087.48   306.5    2088   327.7 2088.98
   347.6 2089.19   466.7 2088.88   525.9 2090.35   565.4 2090.68   575.3 2090.94
   585.2 2091.71     595    2093   614.8 2096.35     674 2108.34   683.9  2110.8
   762.8 2135.45   782.6 2140.66   792.4 2142.76   812.2 2146.32   851.7 2151.71
#Mann= 3 , 0 , 0
       0      .1       0   291.5    .045       0   306.5      .1       0
Bank Sta=291.5,306.5
XS Rating Curve= 0 ,0
Exp/Cntr=0.3,0.1

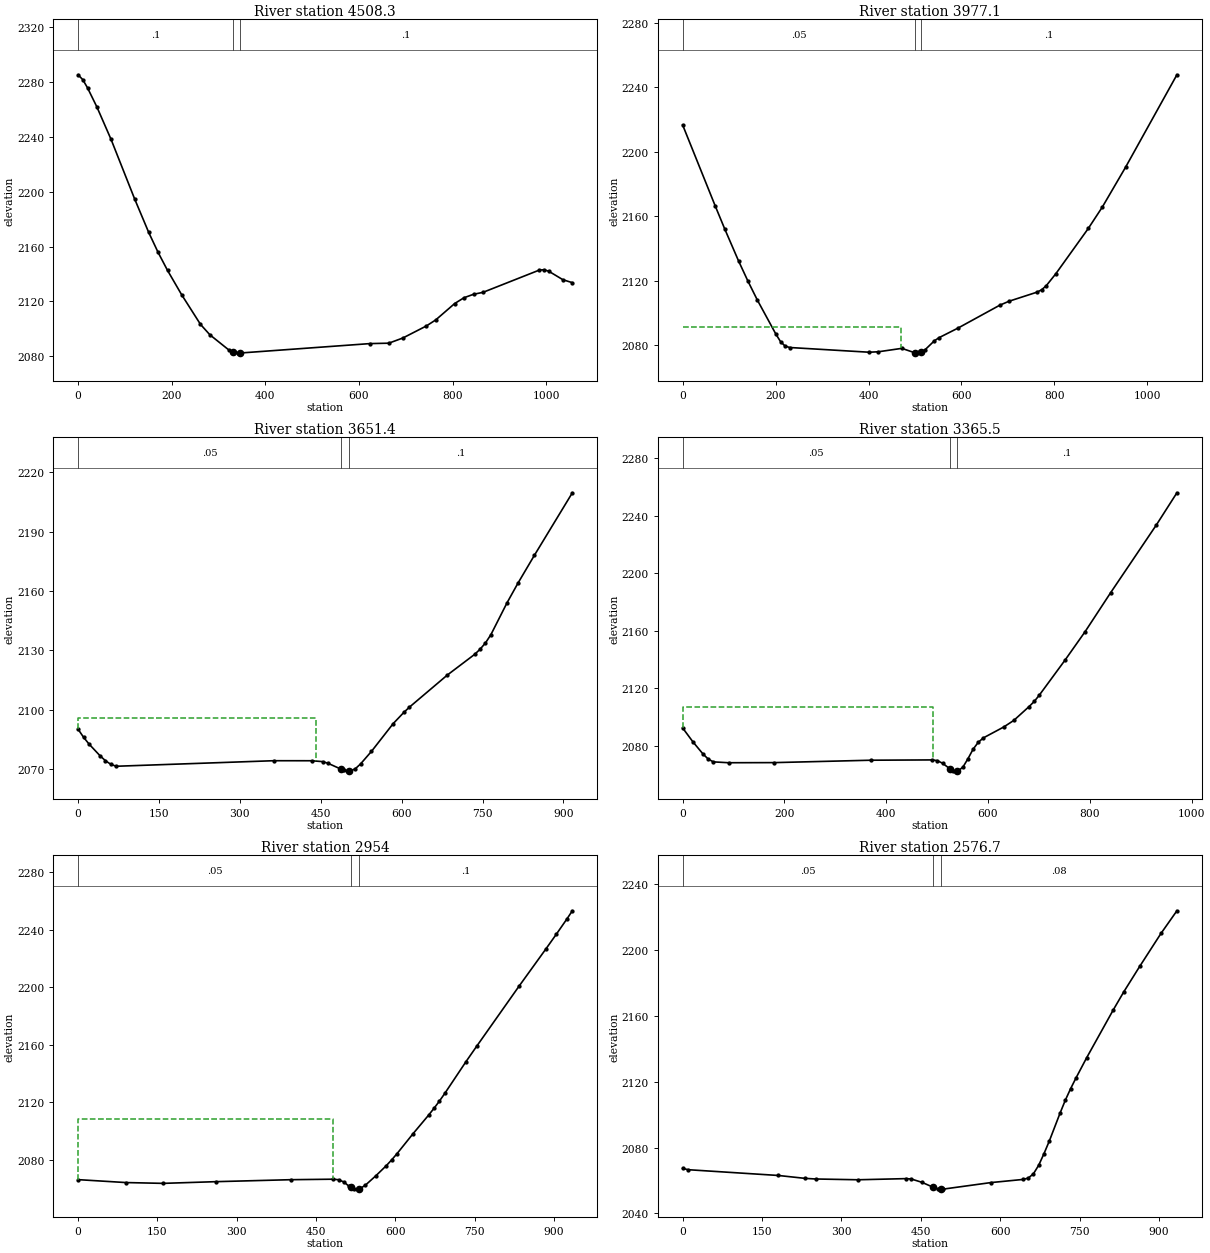
Type RM Length L Ch R = 1 ,4508.3  ,516.9,531.2,545.6
XS GIS Cut Line= 2
     2185877.814       303262.69     2186929.833      303350.766
#Sta/Elev= 30
       0 2285.24      10 2281.69    20.1 2275.73    40.2 2261.72    70.4 2238.12
   120.6 2194.82   150.8 2170.29   170.9  2155.7     191 2142.59   221.2 2124.83
   261.4 2103.25   281.5 2095.63   321.7 2084.65   329.9 2083.11   341.8 2082.28
   344.9 2082.33   623.4 2089.23   663.6 2089.53   693.8 2093.33     744 2102.11
   764.1 2106.55   804.3 2118.43   824.4  2122.7   844.6 2125.19   864.7 2126.59
   985.3 2142.86   995.4 2143.08  1005.4 2141.99  1035.6 2135.81  1055.7 2133.67
#Mann= 3 , 0 , 0
       0      .1       0   329.9    .045       0   344.9      .1       0
Bank Sta=329.9,344.9
XS Rating Curve= 0 ,0
Exp/Cntr=0.3,0.1

Type RM Length L Ch R = 1 ,3977.1  ,324.2,325.7,327.1
XS GIS Cut Line= 2
     2185760.379      303477.987     2186616.674      304109.198
#Sta/Elev= 30
       0 2216.45    70.2 2166.18    90.3 2152.16   120.4  2132.1   140.5 2119.63
   160.6 2107.98   200.7 2086.74   210.8 2082.06   220.8  2079.3   230.8 2078.48
   401.4 2075.56   421.5 2075.85   471.7 2077.96     499 2075.28   501.8    2075
     514 2075.62   521.9 2077.14   541.9 2082.68     552 2084.61   592.1 2090.45
   682.4  2104.7   702.5 2107.19   762.7 2112.81   772.8 2114.32   782.8 2116.88
   802.9 2124.12   873.1 2152.33   903.2 2165.55   953.4 2190.33  1063.8 2247.61
#Mann= 3 , 0 , 0
       0     .05       0     499    .045       0     514      .1       0
#XS Ineff= 2 , 0
           470.3 2091.15
Permanent Ineff=
       F       F
Bank Sta=499,514
XS Rating Curve= 0 ,0
Exp/Cntr=0.3,0.1

Type RM Length L Ch R = 1 ,3651.4  ,280.3,285.9,291.6
XS GIS Cut Line= 2
      2185617.45      303735.055     2186319.241      304324.675
#Sta/Elev= 30
       0 2090.19    10.1 2086.15    20.2 2082.74    40.3 2076.91    50.4 2074.38
    60.4 2072.52    70.5 2071.51   362.6 2074.31   433.1  2074.3   453.3 2073.86
   463.3 2073.03   487.1 2070.11   493.6 2069.38   502.1  2069.1   503.6 2069.05
   513.7 2070.15   523.8 2072.68   543.9 2078.97   584.2 2093.01   604.4  2098.8
   614.4 2101.36   684.9 2117.62   735.3 2128.01   745.4 2130.61   755.4 2133.78
   765.5 2137.96   795.7  2154.2   815.9 2164.08   846.1 2178.02   916.6 2209.65
#Mann= 3 , 0 , 0
       0     .05       0   487.1    .045       0   502.1      .1       0
#XS Ineff= 2 , 0
          442.11 2095.66
Permanent Ineff=
       F       F
Bank Sta=487.1,502.1
XS Rating Curve= 0 ,0
Exp/Cntr=0.3,0.1

Type RM Length L Ch R = 1 ,3365.5  ,411.7,411.5,411.3
XS GIS Cut Line= 2
     2185486.364      303820.505     2186053.966      304608.296
#Sta/Elev= 30
       0 2092.43      20 2082.85      40 2074.32      50 2070.89    60.1 2068.88
    90.1 2068.28   180.2 2068.36   370.4 2070.03   490.5 2070.24   500.5  2069.7
   510.5 2067.94   524.6 2064.16   530.5 2062.73   539.6 2062.47   540.5 2062.44
   550.6 2065.22   560.6 2071.11   570.6 2077.68   580.6 2082.42   590.6 2085.52
   630.6 2093.09   650.6 2097.71   680.7 2107.36   690.7 2110.88   700.7 2115.28
   750.8 2139.42   790.8 2159.49   840.8  2186.5   930.9 2233.75     971 2255.96
#Mann= 3 , 0 , 0
       0     .05       0   524.6    .045       0   539.6      .1       0
#XS Ineff= 2 , 0
          492.25 2107.12
Permanent Ineff=
       F       F
Bank Sta=524.6,539.6
XS Rating Curve= 0 ,0
Exp/Cntr=0.3,0.1

Type RM Length L Ch R = 1 ,2954    ,368.1,377.2,385.1
XS GIS Cut Line= 2
     2185168.312      304089.626     2185721.234      304843.166
#Sta/Elev= 30
       0 2066.22    90.4 2064.19   160.8 2063.63   261.3 2064.82     402 2066.18
   482.4 2066.53   492.4 2066.16   502.5 2064.61   512.5 2061.56   516.2 2060.85
   522.6 2059.62   531.2 2059.88   532.6 2059.92   542.7 2062.19   562.8 2068.83
   582.9 2075.98   592.9 2079.96     603 2084.27   633.1 2098.07   663.3 2111.33
   673.3    2116   683.4 2120.96   693.4 2126.23   733.6 2148.39   753.7 2159.03
   834.1 2200.99   884.4 2226.65   904.5 2237.08   924.6 2247.75   934.6 2253.28
#Mann= 3 , 0 , 0
       0     .05       0   516.2    .045       0   531.2      .1       0
#XS Ineff= 2 , 0
          481.31 2108.52
Permanent Ineff=
       F       F
Bank Sta=516.2,531.2
XS Rating Curve= 0 ,0
Exp/Cntr=0.3,0.1

Type RM Length L Ch R = 1 ,2576.7  ,634.8,626.4,618.8
XS GIS Cut Line= 2
     2185050.877      304133.664     2185236.815      305048.677
#Sta/Elev= 30
       0 2067.44      10 2066.62   180.7 2063.11   230.9 2061.36     251 2060.97
   331.3  2060.5   421.7 2061.19   431.7 2060.98   451.8 2058.97   472.8 2056.02
   481.9 2055.04   487.8 2054.91     492 2054.81   582.3 2058.79   642.6 2060.68
   652.6 2061.47   662.6 2064.09   672.7 2069.37   682.7 2076.43   692.8 2084.15
   712.8 2100.85   722.9 2108.83   732.9 2115.85     743 2122.32     763 2134.52
   813.2 2163.56   833.3 2174.66   863.4 2190.14   903.6 2210.18   933.7 2223.94
#Mann= 3 , 0 , 0
       0     .05       0   472.8    .045       0   487.8     .08       0
Bank Sta=472.8,487.8
XS Rating Curve= 0 ,0
Exp/Cntr=0.3,0.1

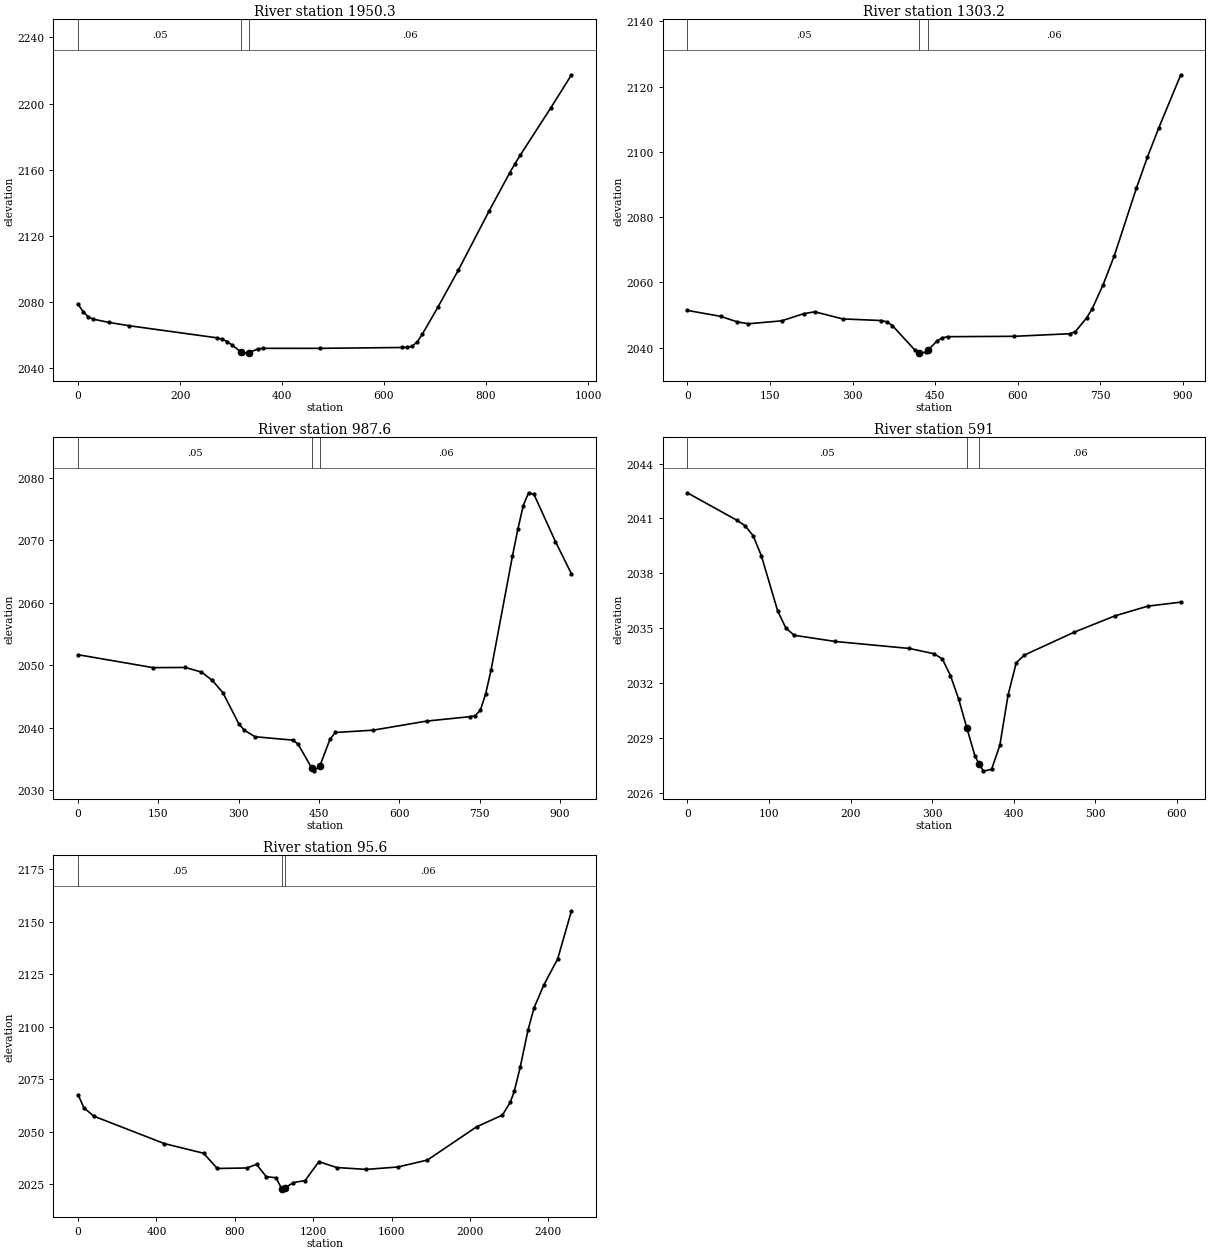
Type RM Length L Ch R = 1 ,1950.3  ,646.5,647.2,647.7
XS GIS Cut Line= 2
     2184419.665      304388.106     2184953.015       305195.47
#Sta/Elev= 30
       0 2078.65    10.1 2074.22    20.2 2071.01    30.2 2069.69    60.5 2067.74
   100.8 2065.71   272.1 2058.44   282.2 2057.65   292.3 2056.18   302.4    2054
     320 2049.73   322.5 2049.18   332.6  2049.2     335 2049.53   352.8 2051.72
   362.9 2052.08   473.7 2052.07     635 2052.59   645.1 2052.65   655.2 2053.34
   665.2 2056.03   675.3 2060.71   705.6 2076.95   745.9 2099.44   806.4 2135.31
   846.7  2158.3   856.8 2163.68   866.8 2168.67   927.3 2197.56   967.6 2217.41
#Mann= 3 , 0 , 0
       0     .05       0     320    .045       0     335     .06       0
Bank Sta=320,335
XS Rating Curve= 0 ,0
Exp/Cntr=0.3,0.1

Type RM Length L Ch R = 1 ,1303.2  ,315.2,315.6,316
XS GIS Cut Line= 2
     2183984.178      304774.662     2184453.917      305537.988
#Sta/Elev= 30
       0  2051.4    60.4 2049.58    90.6 2047.88   110.8  2047.3   171.2  2048.2
   211.5  2050.4   231.6 2050.97     282 2048.79   352.5 2048.29   362.5 2047.89
   372.6 2046.73   412.9 2039.31   421.6 2038.44     423  2038.3     433 2038.61
   436.6 2039.14   453.2 2041.95   463.2 2043.01   473.3 2043.34   594.2 2043.46
   694.9 2044.25   704.9 2044.91   725.1 2049.05   735.2 2051.81   755.3 2059.28
   775.4 2068.06   815.7 2088.86   835.9 2098.46     856  2107.2   896.3 2123.63
#Mann= 3 , 0 , 0
       0     .05       0   421.6    .045       0   436.6     .06       0
Bank Sta=421.6,436.6
XS Rating Curve= 0 ,0
Exp/Cntr=0.3,0.1

Type RM Length L Ch R = 1 ,987.6   ,395.1,396.5,397.8
XS GIS Cut Line= 2
     2183729.736      304945.921     2184199.475      305738.606
#Sta/Elev= 30
       0 2051.69   140.2 2049.62   200.3 2049.65   230.4 2048.91   250.4  2047.6
   270.4 2045.61   300.5 2040.57   310.5  2039.6   330.5 2038.55   400.6 2038.01
   410.6  2037.4   436.6  2033.5   440.7 2033.04   451.6 2033.88   470.7 2038.22
   480.7 2039.23   550.8  2039.6     651 2041.06   731.1 2041.76   741.1  2041.9
   751.2 2042.78   761.2 2045.44   771.2 2049.22   811.2 2067.51   821.3  2071.8
   831.3 2075.59   841.3 2077.63   851.3  2077.4   891.4 2069.83   921.4 2064.64
#Mann= 3 , 0 , 0
       0     .05       0   436.6    .045       0   451.6     .06       0
Bank Sta=436.6,451.6
XS Rating Curve= 0 ,0
Exp/Cntr=0.3,0.1

Type RM Length L Ch R = 1 ,591     ,493.9,495.4,496.8
XS GIS Cut Line= 2
     2183497.694      305253.686     2183768.056      305794.411
#Sta/Elev= 27
       0  2042.4    60.4 2040.91    70.5 2040.61    80.6 2040.06    90.7 2038.96
   110.8 2035.93   120.9    2035     131 2034.62   181.4 2034.28     272  2033.9
   302.3 2033.61   312.4 2033.33   322.4 2032.42   332.5 2031.13   342.6 2029.54
   352.6    2028   357.6  2027.6   362.7  2027.2   372.8  2027.3   382.9 2028.61
     393 2031.35     403 2033.12   413.1 2033.54   473.6 2034.78   523.9 2035.68
   564.2 2036.21   604.6 2036.43
#Mann= 3 , 0 , 0
       0     .05       0   342.6    .045       0   357.6     .06       0
Bank Sta=342.6,357.6
XS Rating Curve= 0 ,0
Exp/Cntr=0.3,0.1

Type RM Length L Ch R = 1 ,95.6    ,80.8,95.6,110.5
XS GIS Cut Line= 4
     2183619.382      304739.577     2183152.551      305601.706
     2183215.827       305757.02     2184536.198      306120.392
#Sta/Elev= 30
       0 2067.54      30 2061.27      80 2057.34   440.2 2044.24   640.3 2039.64
   710.3 2032.37   860.4 2032.61   910.4 2034.32   960.4 2028.45    1010 2027.96
  1039.2 2022.59  1039.6 2022.52  1054.2 2022.96  1098.8 2025.67  1158.2 2026.59
  1228.7 2035.63  1319.3 2032.83  1470.3 2031.93  1631.4 2033.08  1782.5 2036.39
  2034.2 2052.28  2165.1 2057.84  2205.4 2063.97  2225.6 2069.13  2255.8 2080.61
    2296 2098.46  2326.2 2108.86  2376.6 2119.93  2447.1 2132.32  2517.6 2155.28
#Mann= 3 , 0 , 0
       0     .05       0  1039.2    .045       0  1054.2     .06       0
Bank Sta=1039.2,1054.2
XS Rating Curve= 0 ,0
Exp/Cntr=0.3,0.1

Chan Stop Cuts=-1
Use User Specified Reach Order=0
Composite Channel Slope=5